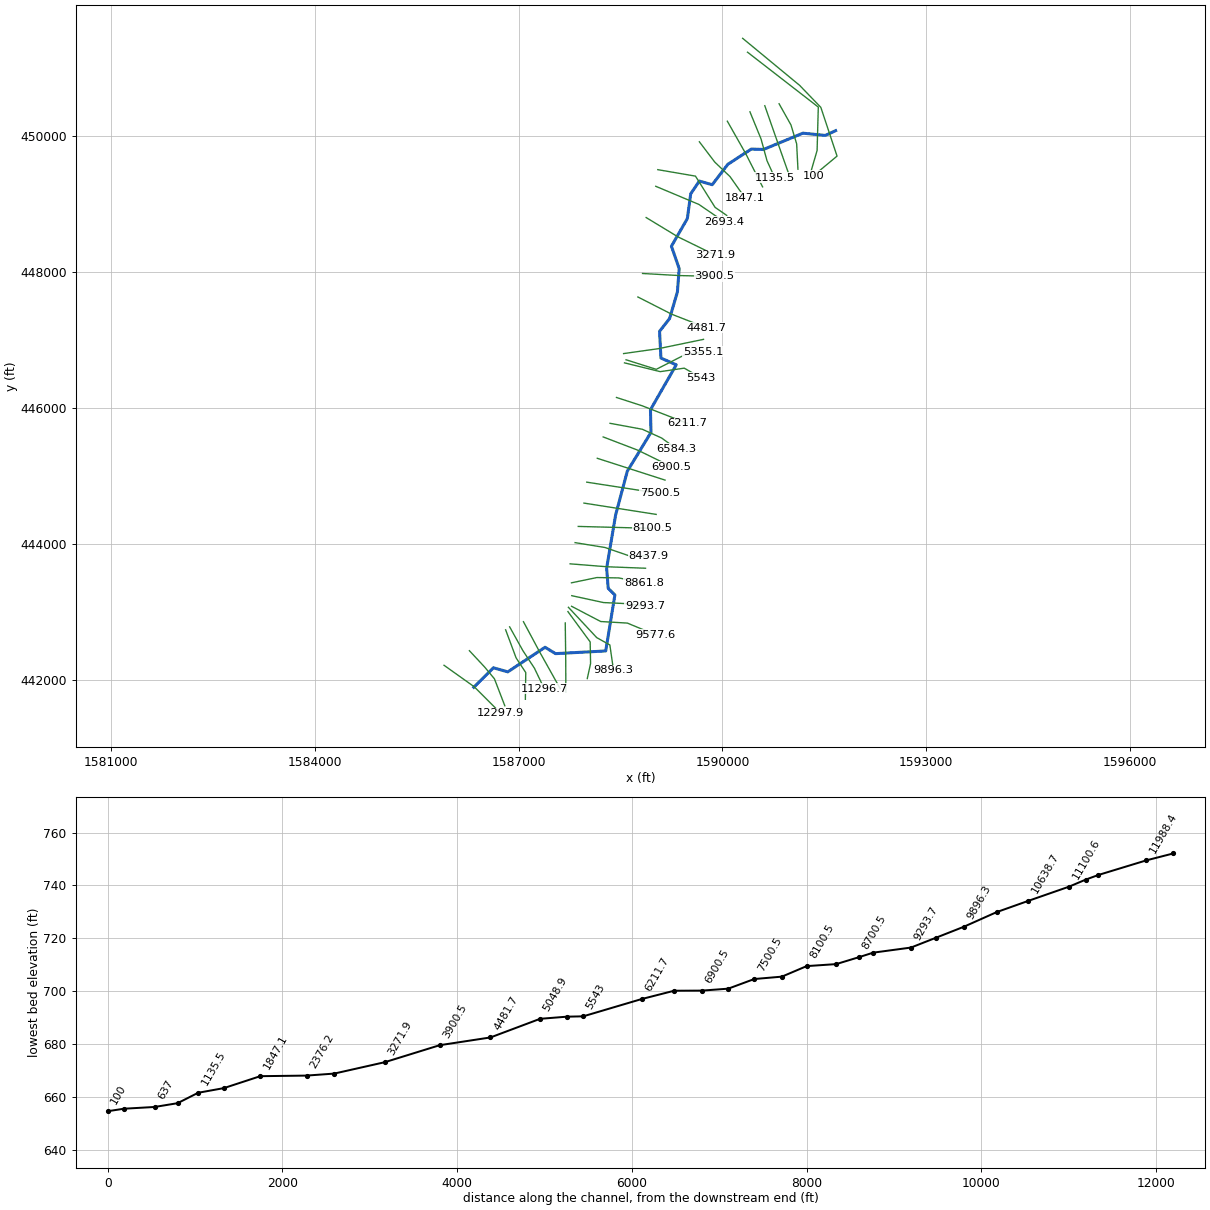
--- RFBEECHFK.prj (project) ---

Proj Title=RFBEECHFK
Current Plan=p01
Default Exp/Contr=0,0
English Units
Geom File=g01
Flow File=f01
Plan File=p01
BEGIN DESCRIPTION:
END DESCRIPTION:
DSS Export Rating Curves= 0
DSS Export Rating Curve Sorted= 0
DSS Export Volume Flow Curves= 0
DXF OffsetX= 0
DXF OffsetY= 0
DXF ScaleX= 0
DXF ScaleY= 0

--- RFBEECHFK.p01 (plan) ---

Plan Title=Floodplain
Program Version=4.00
Geom File=g01
Flow File=f01
K Sum by GR=0
Std Step Tol=0.01
Critical Tol=0.01
Num of Std Step Trials=20
Max Error Tol=0.3
Flow Tol Ratio=0.001
Split Flow NTrial=30
Split Flow Tol=0.02
Split Flow Ratio=0.02
Log Output Level=0
Friction Slope Method=1
Unsteady Friction Slope Method=2
Unsteady Bridges Friction Slope Method=1
Global Log Level=0
CheckData=False
Run HTab=0
Run UNet=0
Run PostProcess=0
UNET Theta=0
UNET Theta Warmup=0
UNET ZTol=0
UNET ZSATol=0
UNET MxIter=0
UNET MaxInSteps=0
UNET DtIC=0
UNET DtMin=0
UNET MaxCRTS=0
UNET WFStab=0
UNET SFStab=0
UNET WFX=0
UNET SFX=0
UNET DSS MLevel=0
UNET DZMax Abort=0
UNET Convert EG Bridges=0
UNET Use Existing IB Tables=0
UNET Froude Limit=0
UNET Froude Power=0
Write IC File=0
Echo Input=False
Echo Output=False
Write Detailed=0

--- RFBEECHFK.f01 (steady flow) ---

Flow Title=NFF Regression Equation
Program Version=4.00
Number of Profiles= 1
Profile Names=P100yr
River Rch & RM=RFBEECHFK,Main            ,12297.9
     415
River Rch & RM=RFBEECHFK,Main            ,9896.3
     442
River Rch & RM=RFBEECHFK,Main            ,9577.6
     685
River Rch & RM=RFBEECHFK,Main            ,9293.7
     694
River Rch & RM=RFBEECHFK,Main            ,6584.3
     765
River Rch & RM=RFBEECHFK,Main            ,5355.1
     848
River Rch & RM=RFBEECHFK,Main            ,4481.7
     931
River Rch & RM=RFBEECHFK,Main            ,3271.9
    1034
River Rch & RM=RFBEECHFK,Main            ,286.6
    1082
Boundary for River Rch & Prof#=RFBEECHFK,Main            , 1
Up Type= 0
Dn Type= 3
Dn Slope=0.0155
DSS Import GetInterval= 0
DSS Import GetPeak= 0
DSS Import FillOption= 0

--- RFBEECHFK.g01 (geometry) ---

Geom Title=USGS 10m DEM
Program Version=4.00

River Reach=RFBEECHFK       ,Main
Reach XY= 30
      1586338.92       441892.66       1586628.6      442179.229
     1586839.942      442119.361     1587388.656      442481.349
     1587542.618      442387.386     1588281.662      442426.946
     1588416.697      443250.979     1588317.946      443348.727
     1588295.364      443646.247     1588427.635      444428.865
     1588599.266       445070.75     1588948.249      445642.584
     1588940.329      445975.609     1589319.895      446636.514
     1589094.653      446736.122     1589074.208      447129.889
     1589222.486      447318.012      1589337.21      447710.219
     1589363.493      448050.816     1589249.012      448382.123
     1589483.167       448787.71     1589533.109      449153.001
     1589660.026       449340.27     1589849.633       449286.29
     1590079.875      449587.173      1590425.03      449810.967
     1590603.997      449804.824     1591184.434      450044.764
     1591514.712      450011.451     1591665.812      450081.413

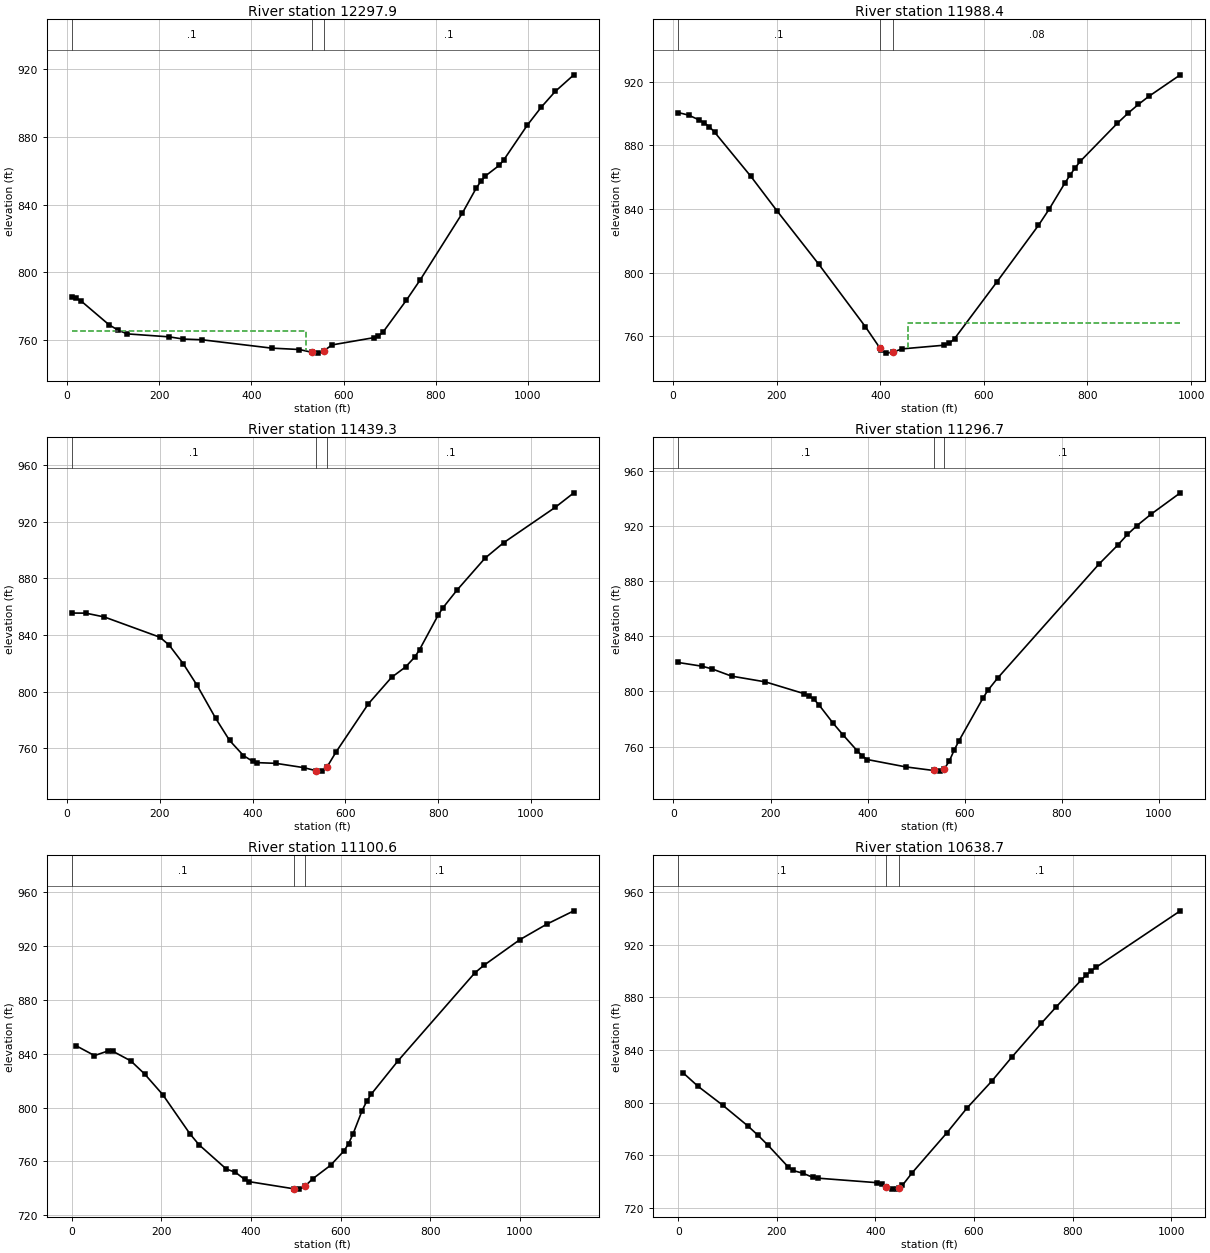
Type RM Length L Ch R = 1 ,12297.9 ,316.6,309.5,307
XS GIS Cut Line= 3
     1585901.043       442216.22     1586344.714       441900.81
      1586737.72      441508.509
#Sta/Elev= 30
    10.1  785.33    20.2  784.55    30.2  782.98    90.7  768.94   110.9  765.64
     131  763.48   221.8  761.73     252  760.43   292.3  760.02   443.6  755.07
     504  754.25   531.9  752.56   544.4  752.11   556.9  753.37   574.6  756.95
   665.5  761.25   675.6  762.26   685.7  764.58   736.2  783.39   766.5  795.52
   857.3  834.71   887.6  849.58   897.7  853.67   907.8  856.91   938.1  863.24
   948.2  866.62   998.7  886.94    1029   897.6  1059.3  906.89  1099.7  916.72
#Mann= 3 , 0 , 0
    10.1      .1       0   531.9    .045       0   556.9      .1       0
#XS Ineff= 2 , 0
          519.33  765.36
Permanent Ineff=
       F       F
Bank Sta=531.9,556.9
XS Rating Curve= 0 ,0
Exp/Cntr=0.3,0.1

Type RM Length L Ch R = 1 ,11988.4 ,551.8,549,546.3
XS GIS Cut Line= 4
     1586274.589      442430.659     1586500.376      442188.779
     1586642.821      442017.846     1586796.028      441620.608
#Sta/Elev= 30
      10  900.59    30.1  898.97    50.1     896    60.2  894.08    70.2  891.64
    80.2  888.26   150.4  860.43   200.5  838.91   280.8  805.52   371.3  766.05
   399.3  752.68   401.7  751.57   411.8  749.49   424.3  750.11   442.1  752.15
   523.1  754.46   533.2  755.63   543.3  758.56   624.4  793.89   705.4  829.76
   725.7  839.75   756.1  856.17   766.3  861.26   776.4  865.98   786.5  870.12
   857.5  893.81   877.8  900.03   898.1  905.67   918.3  910.74   979.2  924.29
#Mann= 3 , 0 , 0
      10      .1       0   399.3    .045       0   424.3     .08       0
#XS Ineff= 2 , 0
                          452.97          768.28
Permanent Ineff=
       F       F
Bank Sta=399.3,424.3
XS Rating Curve= 0 ,0
Exp/Cntr=0.3,0.1

Type RM Length L Ch R = 1 ,11439.3 ,142.6,142.7,142.7
XS GIS Cut Line= 4
     1586808.044      442738.075     1586961.897      442325.526
     1587104.342       442109.01     1587098.644      441715.863
#Sta/Elev= 30
      10  855.46      40  855.41    80.1  852.71   200.1  838.41   220.2  832.78
   250.2  819.81   280.2   804.5   320.2  781.28   350.2  765.66   380.3  754.91
   400.3  750.86   410.3  749.95   450.3  749.46   510.1  746.44   537.5  744.22
     550  743.97   559.9   746.6   579.9  757.47   649.6  791.45   699.5  810.08
   729.7  817.41   749.9  824.52     760  829.68   800.3  854.11   810.4  859.19
   840.6  871.59   901.1  894.16   941.4   905.1  1052.3  929.96  1092.7  940.26
#Mann= 3 , 0 , 0
      10      .1       0   537.5    .045       0   559.9      .1       0
Bank Sta=537.5,559.9
XS Rating Curve= 0 ,0
Exp/Cntr=0.3,0.1

Type RM Length L Ch R = 1 ,11296.7 ,198.6,196.1,194.1
XS GIS Cut Line= 4
     1586867.271      442781.418     1587061.296      442432.781
     1587231.067      442175.093     1587376.585       441871.93
#Sta/Elev= 30
      10  820.99    59.8  818.25    79.8  816.32   119.7  811.12   189.5  806.93
   269.3  798.39   279.3   796.8   289.3  794.36   299.2  790.53   329.2  776.86
   349.1  768.61     379  756.83     389  753.28     399  750.67   478.6  745.31
   535.8  742.71   548.3  742.25   558.3  744.09   568.2  749.54   578.2  757.47
   588.1  764.23   637.9  795.41   647.9  800.93   667.8  809.72   875.7  892.05
   915.3  906.15   935.1  913.82   954.8  920.26   984.5   928.7  1043.9  943.97
#Mann= 3 , 0 , 0
      10      .1       0   535.8    .045       0   558.3      .1       0
Bank Sta=535.8,558.3
XS Rating Curve= 0 ,0
Exp/Cntr=0.3,0.1

Type RM Length L Ch R = 1 ,11100.6 ,476,461.9,447.2
XS GIS Cut Line= 3
      1587070.39      442857.209     1587310.281      442410.035
      1587610.02      441874.961
#Sta/Elev= 30
    10.1  845.73    50.7  838.52    81.2  841.96    91.3  841.77   131.9  834.55
   162.4  824.95     203   809.6   263.9  780.46   284.2  772.36   345.1  754.38
   365.4  751.98   385.7  746.78   395.8  745.06     495   739.8   507.5  739.52
     520  741.49   537.6   747.1   577.8   757.2     608  767.98   618.1  773.33
   628.1  780.61   648.2  797.78   658.3  804.58   668.3  809.82   728.6  834.74
   899.6  899.75   919.7  905.35  1000.1  924.39  1060.4  935.93  1120.8  945.81
#Mann= 3 , 0 , 0
       0      .1       0     495    .045       0     520      .1       0
Bank Sta=495,520
XS Rating Curve= 0 ,0
Exp/Cntr=0.3,0.1

Type RM Length L Ch R = 1 ,10638.7 ,365.3,365.4,365.6
XS GIS Cut Line= 3
     1587685.811      442839.019     1587692.511      442343.992
     1587694.906      441820.392
#Sta/Elev= 30
    10.1  822.53    40.4  812.29    90.9  797.81   141.4  782.19   161.7   775.2
   181.9  767.67   222.3  751.39   232.4  748.41   252.6  746.33   272.8  743.23
   282.9  742.56   404.1  739.08   414.2   737.8     422  736.19   434.5  734.21
   444.6  734.59     447  735.18   454.7  737.07   474.9  746.75   545.4  777.16
   585.7  795.77     636  816.24   676.3   834.3   736.7  860.26   766.9  872.74
   817.3  892.98   827.4  896.76   837.4  900.02   847.5  902.75  1018.7  945.76
#Mann= 3 , 0 , 0
       0      .1       0     422    .045       0     447      .1       0
Bank Sta=422,447
XS Rating Curve= 0 ,0
Exp/Cntr=0.3,0.1

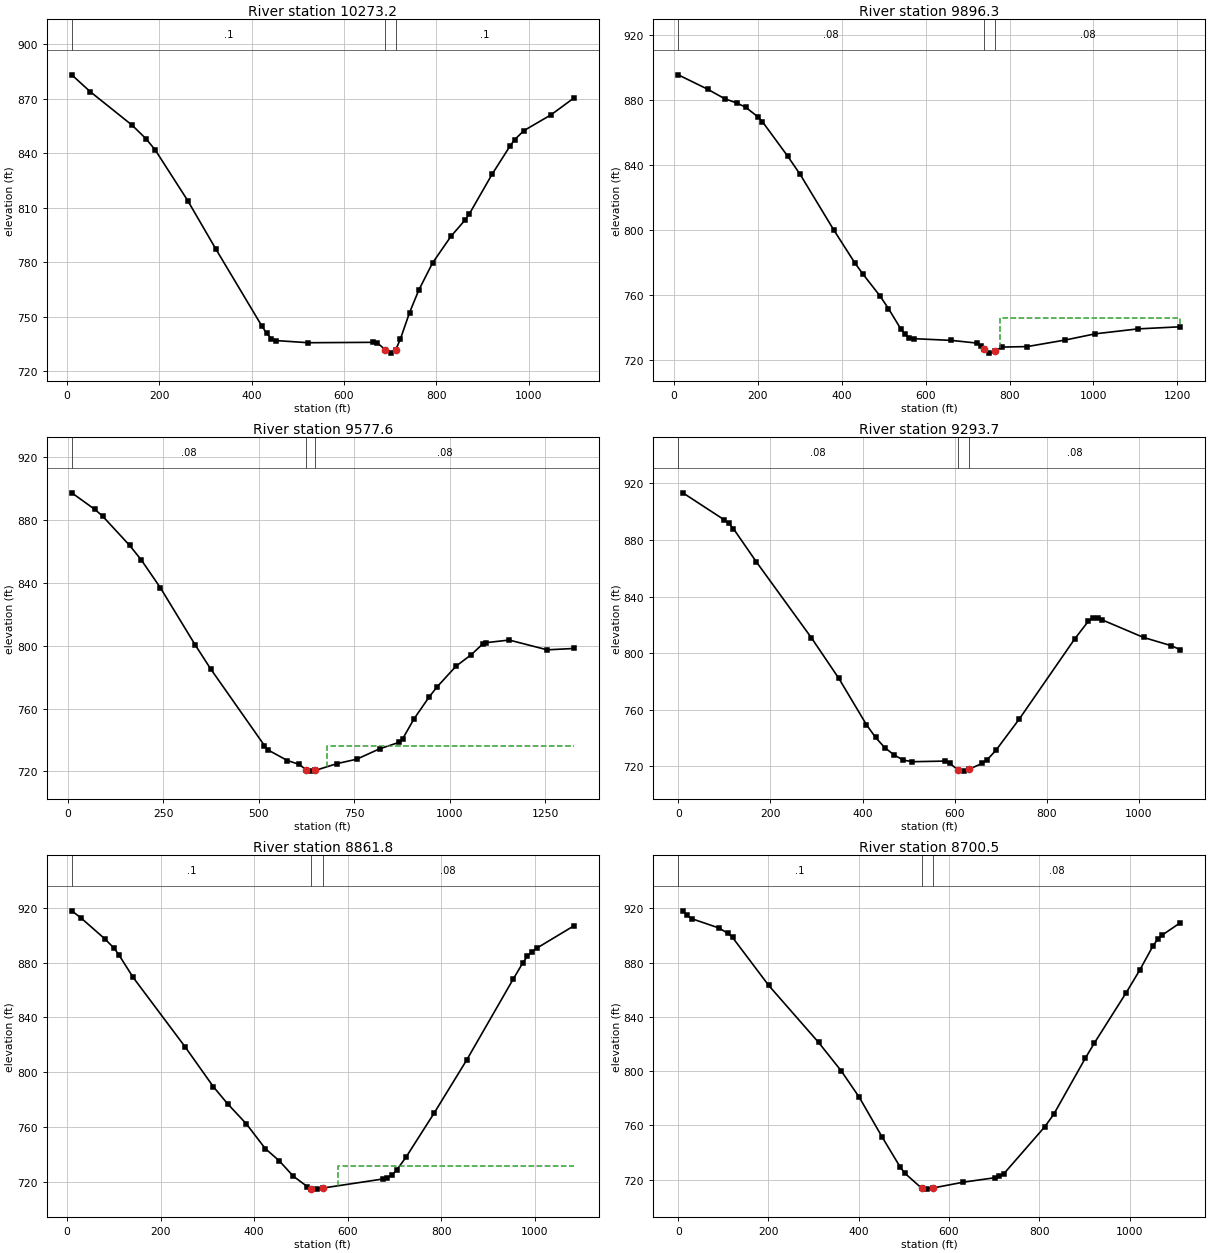
Type RM Length L Ch R = 1 ,10273.2 ,346.7,377,406.9
XS GIS Cut Line= 4
     1587725.222      443005.758     1588052.637      442560.109
     1588058.701      442241.788     1588010.195       442020.48
#Sta/Elev= 30
    10.1  883.27    50.3  873.93   140.8  855.52   170.9  848.06     191  841.85
   261.4  813.92   321.7  787.51   422.3  744.69   432.3  740.89   442.4  737.98
   452.5  736.84   522.8  735.65   662.4  735.87   672.4  735.44   689.7  731.76
   702.2  729.92   712.2  731.91   722.1   737.7     742  752.29   761.9  764.63
   791.8  779.62   831.6  794.27   861.4  803.02   871.4  806.58   920.6  828.42
     960  844.17   969.9  847.62   989.6  852.51  1048.7  861.27  1097.9  870.48
#Mann= 3 , 0 , 0
    10.1      .1       0   689.7    .045       0   712.2      .1       0
Bank Sta=689.7,712.2
XS Rating Curve= 0 ,0
Exp/Cntr=0.3,0.1

Type RM Length L Ch R = 1 ,9896.3  ,305.1,318.7,332.3
XS GIS Cut Line= 4
     1587732.338      443069.189     1588149.744      442622.542
     1588342.471      442515.426     1588396.064      442144.113
#Sta/Elev= 30
      10  895.76    80.2  886.89   120.3  881.11   150.3  878.32   170.4  875.86
   200.4   869.8   210.5  866.97   270.6  845.78   300.7  834.42   380.8  800.21
   430.9  779.98     451  772.81   491.1  759.57   511.1  751.84   541.2  739.04
   551.2  735.89   561.2  733.84   571.2  733.28   661.4  732.21   721.6  730.57
   731.6  728.96   739.1  726.78   751.6  724.37   764.1  725.56   781.7   728.1
     842   728.4   933.2  732.47  1004.2  736.26  1105.6  739.29    1207  740.59
#Mann= 3 , 0 , 0
      10     .08       0   739.1    .045       0   764.1     .08       0
#XS Ineff= 2 , 0
                          777.89          745.98
Permanent Ineff=
       F       F
Bank Sta=739.1,764.1
XS Rating Curve= 0 ,0
Exp/Cntr=0.3,0.1

Type RM Length L Ch R = 1 ,9577.6  ,283.6,283.9,284.3
XS GIS Cut Line= 4
     1587778.967        443083.9     1588208.381      442859.693
     1588599.794      442836.892     1589014.008      442665.886
#Sta/Elev= 30
    10.1  897.35    70.6  886.78    90.8  882.52   161.5  863.91   191.8  854.76
   242.2  836.89     333  800.65   373.4  785.41   514.6  736.49   524.6  733.61
   574.9  726.94   605.1  724.58   622.7  721.26   635.2  720.23   647.7  720.68
   705.6  725.08   755.9   727.8   816.2  734.45   866.4  738.47   876.5  740.86
   906.4  753.57   946.2  767.57   966.1  773.72  1015.9  786.98  1055.8   794.3
  1085.6  801.05  1095.6  802.01  1155.3  803.65  1254.9  797.43  1324.6  798.29
#Mann= 3 , 0 , 0
    10.1     .08       0   622.7    .045       0   647.7     .08       0
#XS Ineff= 2 , 0
                           678.6          735.95
Permanent Ineff=
       F       F
Bank Sta=622.7,647.7
XS Rating Curve= 0 ,0
Exp/Cntr=0.3,0.1

Type RM Length L Ch R = 1 ,9293.7  ,431.3,431.9,432.5
XS GIS Cut Line= 4
     1587781.705      443240.071     1588249.001      443138.889
      1588561.32       443124.32     1588858.203      443089.436
#Sta/Elev= 30
      10  913.36    99.6  894.31   109.6  891.78   119.5  888.13   169.3  864.65
   288.9   810.9   348.6  782.11   408.4  749.45   428.3  740.35   448.2  733.17
   468.2  728.07   488.2  724.36   508.4  723.21     579  723.65   589.1  722.14
   606.8  717.45   619.3  716.55   631.8  717.98   659.7  722.05   669.8  724.32
   689.9  731.44   740.4  753.48   860.5  810.05   890.4  822.68   900.4  824.84
   910.4  824.64   920.3  823.48    1010  811.08  1069.8  805.29  1089.7  802.42
#Mann= 3 , 0 , 0
       0     .08       0   606.8    .045       0   631.8     .08       0
Bank Sta=606.8,631.8
XS Rating Curve= 0 ,0
Exp/Cntr=0.3,0.1

Type RM Length L Ch R = 1 ,8861.8  ,163,161.3,160.7
XS GIS Cut Line= 4
     1587777.345      443429.273     1588152.724      443507.072
     1588473.645      443501.237     1588845.135      443427.329
#Sta/Elev= 30
    10.1  917.85    30.3  912.51    80.7   897.4   100.9  890.44     111  885.59
   141.2  869.25   252.2  818.58   312.7  789.41     343  777.01   383.4  762.22
   423.5  744.28   453.6  735.27   483.7  724.02   513.8  716.41   521.3  715.08
   533.8  714.63   546.3  715.39   674.2  721.99   684.3  722.79   694.3   724.8
   704.3   728.5   724.3  737.88   784.1  769.92   853.8  808.75   953.5  867.98
   973.5  879.53   983.4  884.54   993.4  888.08  1003.4  890.49  1083.1  906.86
#Mann= 3 , 0 , 0
    10.1      .1       0   521.3    .045       0   546.3     .08       0
#XS Ineff= 2 , 0
                          580.12          731.87
Permanent Ineff=
       F       F
Bank Sta=521.3,546.3
XS Rating Curve= 0 ,0
Exp/Cntr=0.3,0.1

Type RM Length L Ch R = 1 ,8700.5  ,269.6,262.6,254.4
XS GIS Cut Line= 3
     1587757.034      443708.749     1588296.917      443665.741
     1588867.469      443643.803
#Sta/Elev= 30
      10  918.25    20.1  914.82    30.1  912.43    90.3  905.57   110.3  901.58
   120.4  898.59   200.6  863.17   310.9  821.21   361.1  800.21   401.2  780.69
   451.3  751.68   491.4  729.47   501.5  724.86   539.1  713.72   551.6  712.94
   564.1  713.76   631.7  718.06   701.9  721.36   711.9  722.29   721.9  724.41
   812.1  758.88   832.1  768.14   902.2   809.6   922.2  820.75   992.4   857.7
  1022.4  874.36  1052.5   892.6  1062.5  897.25  1072.5  900.36  1112.6  909.46
#Mann= 3 , 0 , 0
       0      .1       0   539.1    .045       0   564.1     .08       0
Bank Sta=539.1,564.1
XS Rating Curve= 0 ,0
Exp/Cntr=0.3,0.1

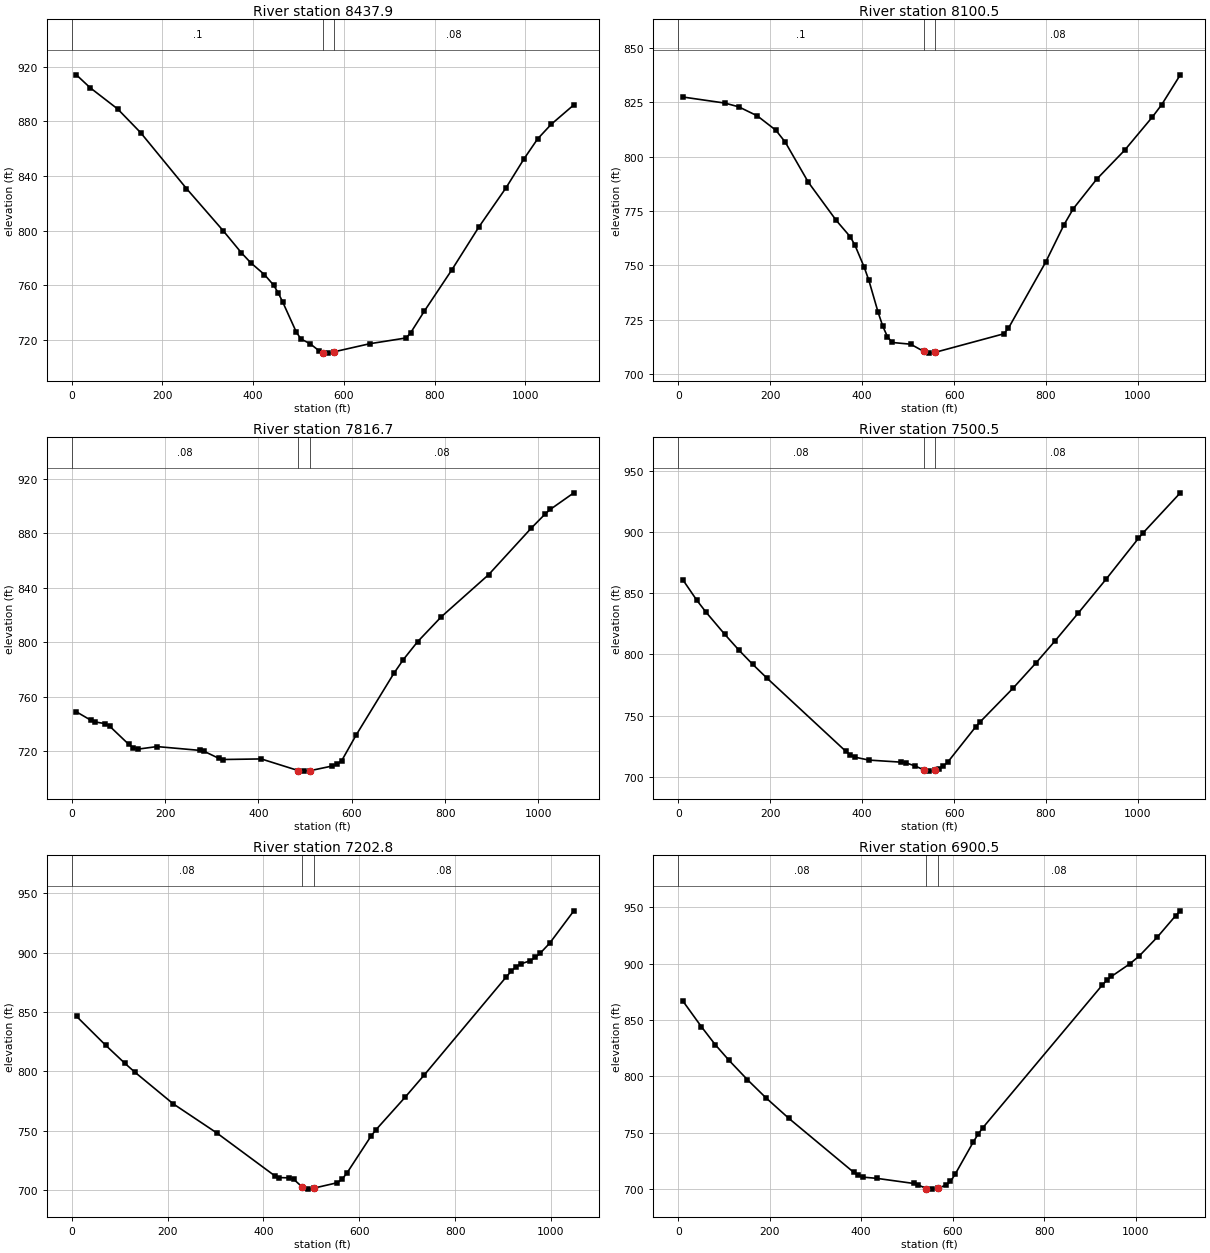
Type RM Length L Ch R = 1 ,8437.9  ,329,337.4,345.8
XS GIS Cut Line= 4
     1587830.862      444020.349     1588270.252      443949.096
     1588632.452      443824.405     1588911.524      443824.405
#Sta/Elev= 30
    10.1  913.98    40.5  904.54   101.2  888.99   151.7  871.72   252.9  830.78
   333.8  799.94   374.3  783.65   394.5  776.51   424.9  767.77   445.1   760.1
   455.2  754.45   465.3  747.63   495.5   725.5   505.6  720.63   525.8  717.13
   545.9   711.9   553.6  710.72   566.1   710.3   578.6  711.27   656.8  717.16
   737.5  721.41   747.5  725.25   777.8  741.16   838.2  771.23     898  802.69
   957.8  831.33   997.6  852.59  1027.5  867.13  1057.4  877.77  1107.3     892
#Mann= 3 , 0 , 0
       0      .1       0   553.6    .045       0   578.6     .08       0
Bank Sta=553.6,578.6
XS Rating Curve= 0 ,0
Exp/Cntr=0.3,0.1

Type RM Length L Ch R = 1 ,8100.5  ,287.4,283.8,280.2
XS GIS Cut Line= 3
     1587877.025      444259.037      1588422.84      444244.817
     1588968.655      444230.597
#Sta/Elev= 30
    10.1  827.49   101.1  824.71   131.4  822.99   171.9  818.82   212.3   812.2
   232.6  806.77   283.1  788.19   343.8  770.63   374.1  763.14   384.2  759.32
   404.4  749.16   414.6  743.07   434.8   728.3   444.9  721.93     455  717.14
   465.1  714.46   505.6  713.66   533.5  710.39     546  709.55   558.5   709.9
   707.8  718.43   717.9  720.93   798.8  751.31   839.2  768.74   859.4  776.11
     910  789.62   970.7  802.94  1031.3   818.3  1051.6     824    1092  837.71
#Mann= 3 , 0 , 0
       0      .1       0   533.5    .045       0   558.5     .08       0
Bank Sta=533.5,558.5
XS Rating Curve= 0 ,0
Exp/Cntr=0.3,0.1

Type RM Length L Ch R = 1 ,7816.7  ,316.1,316.2,316.2
XS GIS Cut Line= 2
     1587961.492      444602.244      1589024.34      444435.988
#Sta/Elev= 30
    10.1  748.99    40.6  742.94    50.7  741.58      71   740.4    81.2  738.52
   121.8  725.28   131.9  722.73   142.1   721.7   182.7  723.56     274  720.79
   284.2  719.98   314.6  715.03   324.8  714.09     406  714.51   484.8  706.03
   497.3  705.57   509.8  705.83   558.2  709.33   568.3  710.44   578.5  713.31
   608.9  731.77   690.1   777.2   710.4   787.3   740.9  800.39   791.6  818.62
   893.1  849.53   984.4  883.62  1014.9  894.24    1025  897.33  1075.8  909.55
#Mann= 3 , 0 , 0
       0     .08       0   484.8    .045       0   509.8     .08       0
Bank Sta=484.8,509.8
XS Rating Curve= 0 ,0
Exp/Cntr=0.3,0.1

Type RM Length L Ch R = 1 ,7500.5  ,302,297.7,293.4
XS GIS Cut Line= 3
     1588002.511      444910.241     1588542.126      444826.987
     1589081.741      444743.733
#Sta/Elev= 30
    10.1  860.86    40.4  844.19    60.7  834.33   101.1  816.41   131.4   803.7
   161.8  791.93   192.1  780.92     364  721.02   374.1  717.92   384.2  716.09
   414.6  713.69   485.3  711.98   495.4  711.42   515.7  708.81   533.5  705.77
     546  704.67   558.5  705.52   566.2   706.6   576.3  708.69   586.4  712.13
   647.1  740.91   657.2  745.08     728  772.31   778.6  793.24     819  810.75
   869.6  833.53   930.2  861.23    1001  894.77  1011.1  899.22    1092  931.91
#Mann= 3 , 0 , 0
       0     .08       0   533.5    .045       0   558.5     .08       0
Bank Sta=533.5,558.5
XS Rating Curve= 0 ,0
Exp/Cntr=0.3,0.1

Type RM Length L Ch R = 1 ,7202.8  ,303.7,302.3,298.4
XS GIS Cut Line= 2
     1588157.436      445261.328     1589154.969      444940.692
#Sta/Elev= 30
    10.1  846.27    70.5  822.12   110.8  806.84     131  799.62   211.6   772.8
   302.2  748.41   423.1   712.4   433.2  710.73   453.4  710.52   463.4  709.21
   481.2  702.72   483.6  701.82   493.7  701.03   506.2  701.95   554.1  706.41
   564.2  709.39   574.3   714.6   624.6  745.66   634.7  750.91   695.2   778.1
   735.5  796.97   906.7  879.49   916.8  884.16   926.9  888.04     937   890.4
   957.1  893.16   967.2  895.84   977.3  899.32   997.4  907.87  1047.8  935.08
#Mann= 3 , 0 , 0
       0     .08       0   481.2    .045       0   506.2     .08       0
Bank Sta=481.2,506.2
XS Rating Curve= 0 ,0
Exp/Cntr=0.3,0.1

Type RM Length L Ch R = 1 ,6900.5  ,317.9,316.2,317
XS GIS Cut Line= 3
     1588244.663      445575.338     1588753.628      445380.968
      1589250.17      445138.221
#Sta/Elev= 30
    10.1   866.8    50.4  844.19    80.7  828.26     111  814.29   151.3  797.14
   191.7  781.14   242.1  762.82   383.4  715.23   393.5  712.42   403.6  710.91
   433.8  709.84   514.5  705.32   524.6  704.02   542.4  700.74   554.9  700.29
   567.4  701.45     585  703.56   595.1  707.05   605.1  713.33   645.3  742.25
   655.4   748.9   665.4  754.44   926.7  880.81   936.7  885.13   946.8  888.52
     987   899.7  1007.1  906.38  1047.3   923.4  1087.5  942.45  1097.5  946.64
#Mann= 3 , 0 , 0
       0     .08       0   542.4    .045       0   567.4     .08       0
Bank Sta=542.4,567.4
XS Rating Curve= 0 ,0
Exp/Cntr=0.3,0.1

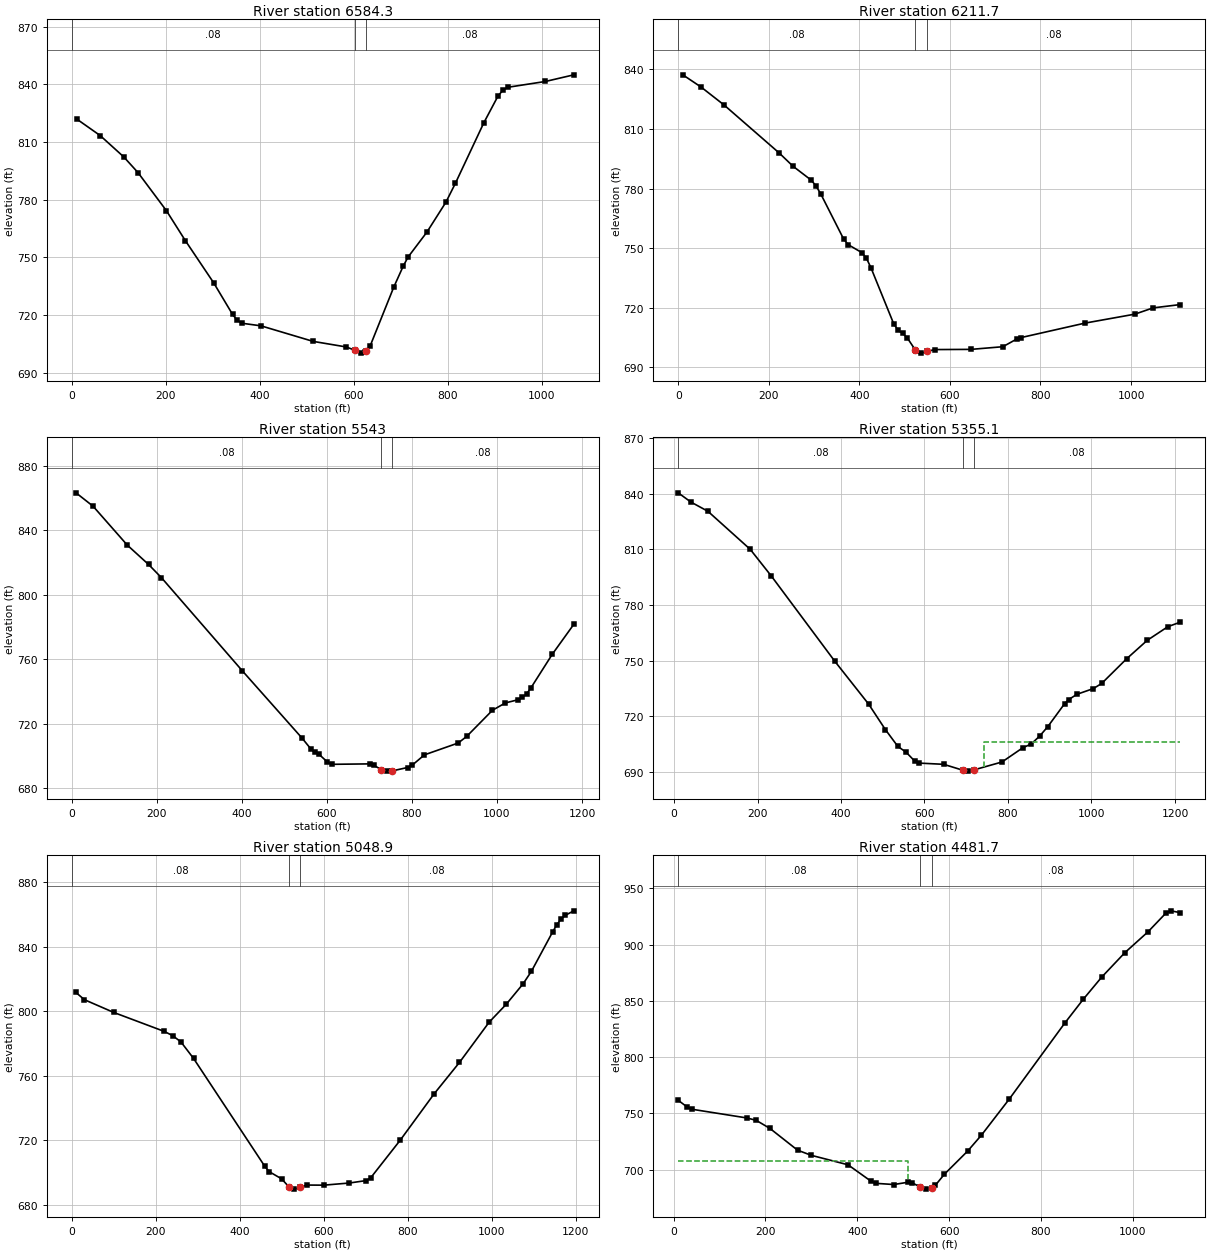
Type RM Length L Ch R = 1 ,6584.3  ,371.3,372.6,373.9
XS GIS Cut Line= 4
     1588345.186      445776.127     1588820.202      445688.724
     1589105.212       445559.52     1589325.619      445399.914
#Sta/Elev= 30
    10.1  822.04    60.4  813.38   110.7  802.25   140.9  794.11   201.2  774.36
   241.5  758.78   301.9  736.79   342.1  720.35   352.2  717.25   362.2  715.78
   402.5  714.44   513.3  706.36   583.9  703.46   601.7  701.79   614.2  700.25
   624.3  700.65   626.7   701.4   634.4  703.79   684.9  734.54   705.1  745.51
   715.2  750.15   755.5  763.19   795.9  778.74   816.1  788.59   876.5  820.01
   906.8  833.98   916.9   836.9   926.9  838.45  1007.6   841.5    1068  844.95
#Mann= 3 , 0 , 0
       0     .08       0   601.7    .045       0   626.7     .08       0
Bank Sta=601.7,626.7
XS Rating Curve= 0 ,0
Exp/Cntr=0.3,0.1

Type RM Length L Ch R = 1 ,6211.7  ,650.4,668.6,688.1
XS GIS Cut Line= 3
     1588440.189       446156.14     1588816.402      446034.536
     1589481.424      445776.127
#Sta/Elev= 30
    10.1   837.3    50.7   831.1   101.4  822.07     223  797.92   253.4  791.27
     294  784.19   304.1  781.36   314.3  777.51     365   754.7   375.1  751.77
   405.4  747.76   415.5  744.95   425.5  740.18   475.8  711.91   485.8  708.55
   495.9  707.02   505.9  704.74   523.6   698.7     526  697.99   536.1  697.11
   548.6  697.94   566.2   698.9   646.6     699   716.9  700.34   747.1  704.15
   757.1  704.94   897.8  712.21  1008.4  716.74  1048.5  719.89  1108.8  721.57
#Mann= 3 , 0 , 0
       0     .08       0   523.6    .045       0   548.6     .08       0
Bank Sta=523.6,548.6
XS Rating Curve= 0 ,0
Exp/Cntr=0.3,0.1

Type RM Length L Ch R = 1 ,5543    ,194.8,187.9,181.9
XS GIS Cut Line= 4
     1588557.993      446665.357     1589084.322      446536.189
     1589437.584      446587.469     1589682.589      446447.874
#Sta/Elev= 30
      10  863.36    50.2  855.02   130.5  830.92   180.6  818.88   210.8  810.72
   401.4  752.78   541.9     711   561.8  704.52   571.7  702.23   581.6  701.01
   601.4   696.2   611.4  694.81   700.6  695.08   710.5  694.24   727.8  691.51
   740.3  690.58   752.8  690.67   789.8  692.83   799.8  694.08   829.5  700.68
     909  708.05   929.1  712.19   989.5  728.37  1019.8  732.92    1050  734.92
    1060  736.38  1070.1  738.62  1080.2  742.37  1130.5  763.26  1180.9  781.76
#Mann= 3 , 0 , 0
       0     .08       0   727.8    .045       0   752.8     .08       0
Bank Sta=727.8,752.8
XS Rating Curve= 0 ,0
Exp/Cntr=0.3,0.1

Type RM Length L Ch R = 1 ,5355.1  ,300.3,306.2,310.5
XS GIS Cut Line= 4
     1588580.794      446710.958     1589025.409      446570.354
     1589443.423      446783.161     1589717.032      446828.762
#Sta/Elev= 30
    10.1  840.39    40.5  835.41    81.1  830.46   182.5  809.96   233.2  795.54
   385.2  749.63   466.3  726.52   506.2  712.86   536.2  703.76   556.1  700.61
   576.1  695.96   586.1  694.79     646  694.12   693.3  690.83  705.33  690.45
   718.3  691.11   785.7  695.38   835.6  703.06   855.5  705.03   875.5  709.24
   895.5  714.46   935.4  726.72   945.3  728.98   965.1  731.84  1004.7  734.94
  1024.5   737.7    1084  750.93  1133.5  760.91    1183  768.28  1212.8  770.72
#Mann= 3 , 0 , 0
    10.1     .08       0   693.3    .045       0   718.3     .08       0
#XS Ineff= 2 , 0
                          741.52          706.34
Permanent Ineff=
       F       F
Bank Sta=693.3,718.3
XS Rating Curve= 0 ,0
Exp/Cntr=0.3,0.1

Type RM Length L Ch R = 1 ,5048.9  ,584.5,567.2,550.8
XS GIS Cut Line= 3
     1588544.941      446801.967      1589059.61      446874.364
     1589721.365      447011.167
#Sta/Elev= 30
      10  811.51      30  807.06    99.9  799.15   219.9  787.42   239.9  784.83
   259.9  780.89   289.9  770.69   459.8  703.71   469.8  700.51   499.7     696
   517.3  690.96   529.8  689.64   542.3  690.74   560.1  692.16   600.4   692.1
   660.9  693.43   701.3  694.95   711.4  696.53     782  719.94   862.7  748.66
   923.2  768.19   993.8  793.11  1034.1  804.09  1074.5  816.83  1094.6   824.7
  1145.1   849.1  1155.1  853.57  1165.2  857.05  1175.3  859.37  1195.5  862.13
#Mann= 3 , 0 , 0
       0     .08       0   517.3    .045       0   542.3     .08       0
Bank Sta=517.3,542.3
XS Rating Curve= 0 ,0
Exp/Cntr=0.3,0.1

Type RM Length L Ch R = 1 ,4481.7  ,569.8,581.2,591.3
XS GIS Cut Line= 3
     1588755.145      447634.681      1589253.81      447380.828
     1589760.397      447183.134
#Sta/Elev= 30
      10  761.63      30  755.44      40  753.64   159.9  745.88   179.9  743.78
   209.8  736.56   269.8  717.27   299.8  712.67   379.7  704.27   429.7  689.69
   439.7  687.78   479.6   686.7   509.6   688.7   519.6  688.15   537.1  684.52
   549.6  682.61   562.1   683.7   569.6  685.85   589.8  695.94   640.1  716.38
   670.3  730.62   730.8  762.65   851.6  830.17   891.9  851.39   932.2  871.16
   982.5  892.87  1032.9   911.4  1073.1  928.57  1083.2  930.13  1103.4  928.48
#Mann= 3 , 0 , 0
      10     .08       0   537.1    .045       0   562.1     .08       0
#XS Ineff= 2 , 0
          510.49  707.73
Permanent Ineff=
       F       F
Bank Sta=537.1,562.1
XS Rating Curve= 0 ,0
Exp/Cntr=0.3,0.1

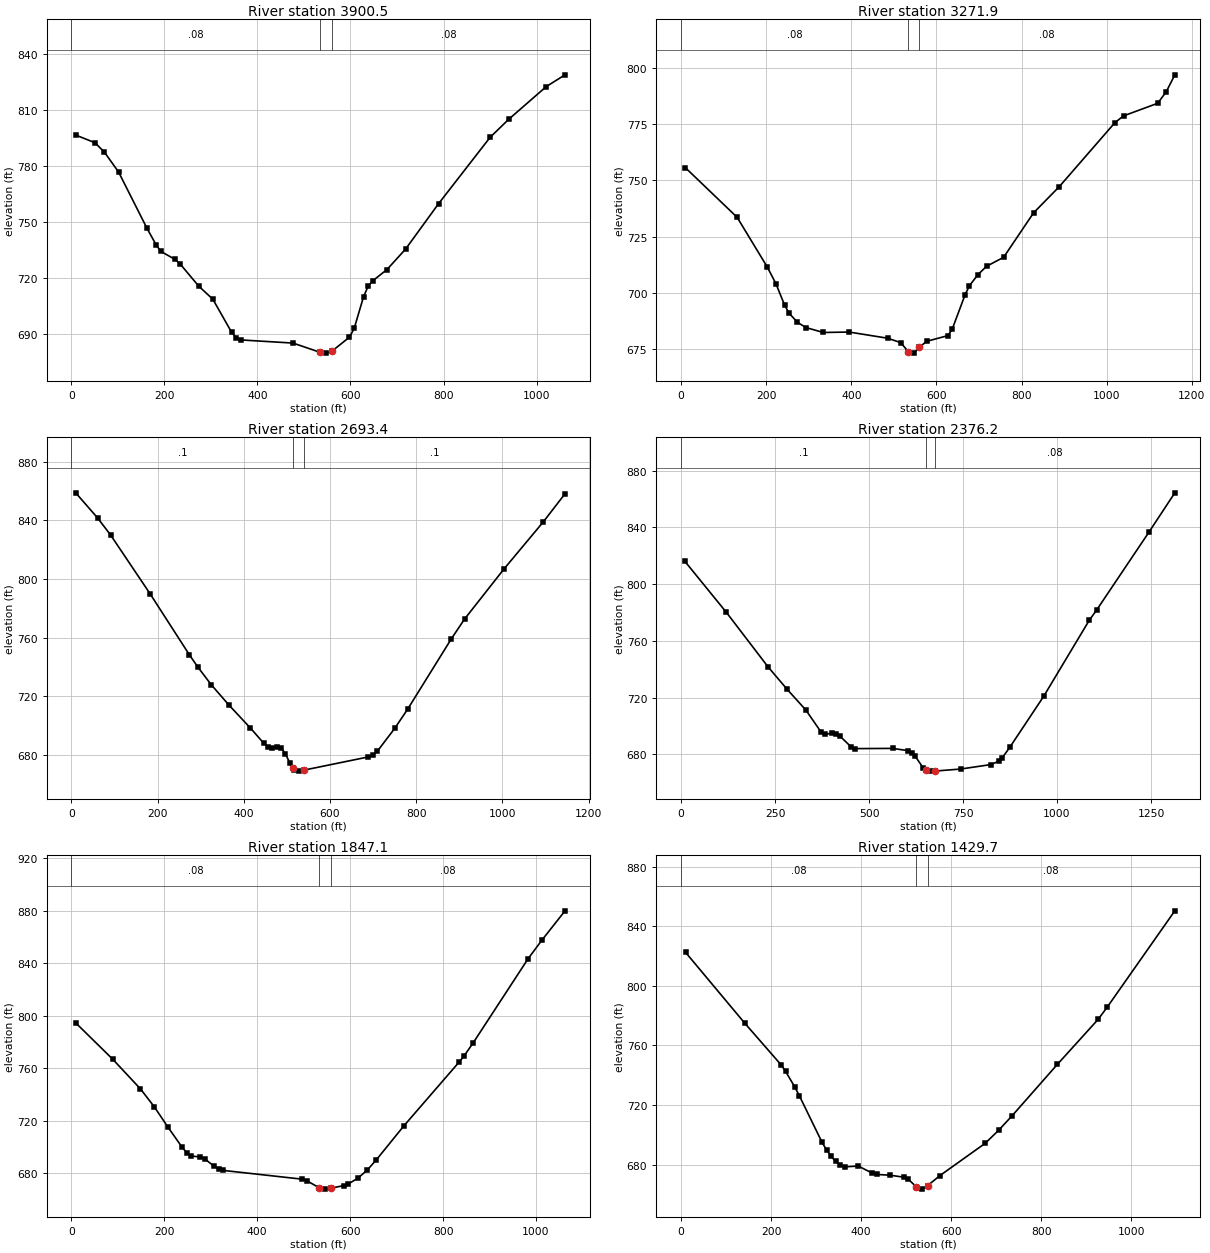
Type RM Length L Ch R = 1 ,3900.5  ,642.4,628.6,615.9
XS GIS Cut Line= 3
     1588824.002      447980.201      1589370.62      447949.446
     1589884.238        447938.4
#Sta/Elev= 30
    10.1  796.31    50.7  792.28      71  787.24   101.4  776.66   162.2  746.66
   182.5  737.49   192.6  734.07     223  729.83   233.2  727.59   273.7  715.55
   304.2  708.51   344.7  690.74   354.8  687.86     365  686.73   476.5  685.06
     535  680.09   547.5  679.68     560  680.69   597.8  688.23   607.9  692.87
   628.1  709.86   638.1  715.56   648.2  718.46   678.4  724.39   718.7  735.44
   789.2  759.61     900  795.12   940.3  804.85  1020.9  822.33  1061.2  828.61
#Mann= 3 , 0 , 0
       0     .08       0     535    .045       0     560     .08       0
Bank Sta=535,560
XS Rating Curve= 0 ,0
Exp/Cntr=0.3,0.1

Type RM Length L Ch R = 1 ,3271.9  ,574.4,578.5,580.5
XS GIS Cut Line= 3
     1588876.938      448803.163      1589344.62       448519.82
     1589895.638      448250.011
#Sta/Elev= 30
    10.1  755.64   131.6  733.62   202.5  711.51   222.8  704.11     243  694.67
   253.2  691.13   273.4  686.93   293.7   684.6   334.2  682.43   394.9  682.63
   486.1  679.86   516.4  677.89   534.3  673.79   546.8  673.26   559.3  675.79
     577   678.5   627.3  681.06   637.3  684.01   667.5  699.25   677.6  703.24
   697.7  708.15   717.8  711.85     758  715.85   828.4  735.62   888.8  747.25
  1019.5  775.68  1039.7  778.68  1120.1  784.29  1140.2  789.43  1160.3  796.93
#Mann= 3 , 0 , 0
       0     .08       0   534.3    .045       0   559.3     .08       0
Bank Sta=534.3,559.3
XS Rating Curve= 0 ,0
Exp/Cntr=0.3,0.1

Type RM Length L Ch R = 1 ,2693.4  ,334,317.2,300.3
XS GIS Cut Line= 3
     1589018.402      449263.338     1589653.736      448996.142
      1590030.18      448738.574
#Sta/Elev= 30
    10.1  858.78    60.8  841.68    91.2  829.94   182.4  790.04   273.7  748.36
   293.9  739.78   324.3  727.99   364.9  714.25   415.6   698.3     446   688.1
   456.1  685.39   466.2   684.9   476.4  685.52   486.5  684.88   496.7   680.8
   506.8  674.55   514.6  671.06   516.9  670.03   527.1  668.96   539.6  669.64
   689.2  678.66   699.4   679.8   709.5  682.37   750.1  698.06   780.5  711.33
   881.8  759.28   912.2  772.65  1003.5  806.75  1094.7  838.88  1145.4  858.15
#Mann= 3 , 0 , 0
       0      .1       0   514.6    .045       0   539.6      .1       0
Bank Sta=514.6,539.6
XS Rating Curve= 0 ,0
Exp/Cntr=0.3,0.1

Type RM Length L Ch R = 1 ,2376.2  ,522.6,529.1,538.8
XS GIS Cut Line= 4
      1589048.21      449507.853     1589603.028       449412.85
     1589891.838      448953.034     1590062.844       448835.23
#Sta/Elev= 30
    10.1  816.09   120.6  780.07   231.2  741.73   281.4  726.07   331.7  711.32
   371.9  695.94     382  694.19   402.1  694.96   412.1  694.71   422.2  693.01
   452.3  685.26   462.4  684.07   562.9  684.23   603.1  682.66   613.2  681.29
   623.2  678.55   643.3  670.73   650.9  669.05   663.4   668.2   675.9  668.25
   743.9  669.68   824.3  672.83   844.4  675.12   854.5  677.62   874.6  685.06
   965.1  721.16  1085.8  774.55  1105.9  781.97  1244.3  836.58  1313.5  864.44
#Mann= 3 , 0 , 0
       0      .1       0   650.9    .045       0   675.9     .08       0
Bank Sta=650.9,675.9
XS Rating Curve= 0 ,0
Exp/Cntr=0.3,0.1

Type RM Length L Ch R = 1 ,1847.1  ,425.4,417.3,408.7
XS GIS Cut Line= 4
      1589660.03      449918.267     1589888.038      449618.057
     1590112.246       449405.25     1590328.853      449097.439
#Sta/Elev= 30
     9.9  794.36    89.3  766.78   148.8  744.24   178.6   730.6   208.3  714.96
   238.1  700.01     248  695.84   257.9  693.24   277.8  692.39   287.7  690.85
   307.5  685.32   317.5  683.23   327.4   682.2   496.6  675.57   506.6  674.39
     534   668.9   546.5  667.98     559  668.73   586.4  670.68   596.4     672
   616.3  676.23   636.2  682.25   656.2  690.21   715.8   716.2   834.7  764.78
   844.6   769.1   864.4  779.11   983.2  843.49    1013  857.65  1062.5  879.84
#Mann= 3 , 0 , 0
       0     .08       0     534    .045       0     559     .08       0
Bank Sta=534,559
XS Rating Curve= 0 ,0
Exp/Cntr=0.3,0.1

Type RM Length L Ch R = 1 ,1429.7  ,301.3,294.3,287.8
XS GIS Cut Line= 3
     1590072.443      450220.329     1590341.311      449746.246
     1590591.335      449254.603
#Sta/Elev= 30
    10.1  822.42   141.3  774.95     222  746.97   232.1  742.52   252.3  732.13
   262.4  726.32   312.9  694.96     323   689.8   333.1  685.54   343.2  682.06
   353.3  679.59   363.3  678.44   393.6  678.96   423.9   674.3     434  673.35
   464.3  672.81   494.6  671.48   504.6  670.09   522.4  665.01   524.8   664.3
   534.9  663.47   547.4   665.8   575.1  672.62   675.4  694.25   705.5  703.07
   735.6  712.89   835.8  747.31   926.1  777.45   946.2  785.61  1096.6  850.41
#Mann= 3 , 0 , 0
       0     .08       0   522.4    .045       0   547.4     .08       0
Bank Sta=522.4,547.4
XS Rating Curve= 0 ,0
Exp/Cntr=0.3,0.1

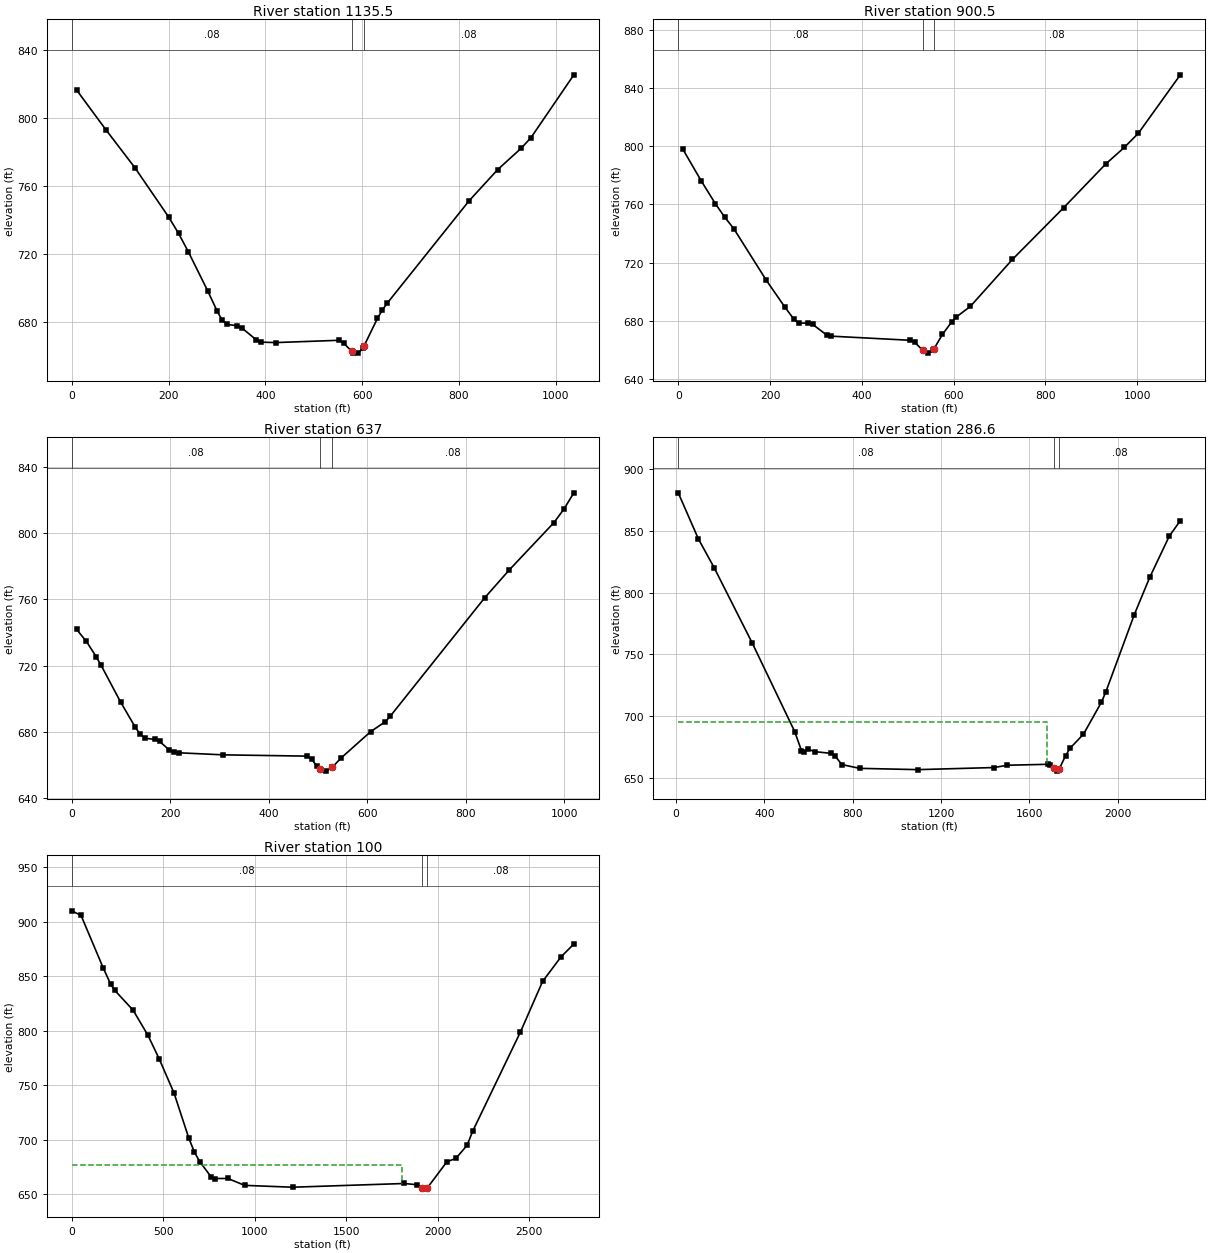
Type RM Length L Ch R = 1 ,1135.5  ,233,235,237
XS GIS Cut Line= 4
     1590404.855      450359.082     1590568.261      449960.068
     1590655.664      449640.857     1590769.668      449390.049
#Sta/Elev= 30
      10  816.64    70.2  793.37   130.4  770.92   200.5  741.74   220.6  732.27
   240.7   721.5   280.8  698.43   300.8  686.26   310.8  681.03   320.9  678.63
   340.9  677.89     351  676.66     381  669.59   391.1  668.19   421.1  667.92
   551.5  669.26   561.6  667.63   579.1  662.69   581.6  662.03   591.6  661.71
   601.7  664.57   604.1  665.99   631.8  682.22   641.8   687.1   651.8  691.08
   821.2  751.44   880.2  769.78   929.4  782.53   949.1  788.63  1037.6  825.59
#Mann= 3 , 0 , 0
       0     .08       0   579.1    .045       0   604.1     .08       0
Bank Sta=579.1,604.1
XS Rating Curve= 0 ,0
Exp/Cntr=0.3,0.1

Type RM Length L Ch R = 1 ,900.5   ,264.7,263.5,262.3
XS GIS Cut Line= 3
     1590623.708      450448.494     1590803.868      449934.083
     1590986.275       449416.65
#Sta/Elev= 30
    10.1  797.76    50.5  775.86    80.7  760.48   100.9   751.3   121.1   743.2
   191.8  707.84   232.1  689.48   252.3  680.92   262.4  678.29   282.6  678.52
   292.7  677.55     323  670.29   333.1  669.43   504.7  666.61   514.8  665.31
   532.5  659.77     535  658.95     545  657.78   555.2  659.82   557.5  660.95
   575.5   670.6   595.8  679.28     606  682.65   636.5  689.92   727.9  722.09
   839.7  757.68   931.1  787.62   971.8  799.08  1002.3  808.75  1093.7  848.89
#Mann= 3 , 0 , 0
       0     .08       0   532.5    .045       0   557.5     .08       0
Bank Sta=532.5,557.5
XS Rating Curve= 0 ,0
Exp/Cntr=0.3,0.1

Type RM Length L Ch R = 1 ,637     ,359.3,350.4,341.5
XS GIS Cut Line= 4
      1590834.27      450476.886     1591009.076      450165.275
     1591092.679      449887.866     1591111.679      449515.453
#Sta/Elev= 30
     9.9   741.8    29.8  734.57    49.6  725.37    59.5  720.23    99.2  698.03
     129  682.84   138.9  678.55   148.9  676.19   168.7  675.49   178.6  674.24
   198.5  668.98   208.4  667.79   218.3   667.4   307.7  666.17   477.2   665.4
   487.2   663.7   497.2  659.45   504.6   657.5   507.2  656.81   517.1  656.35
   529.6  658.82   547.1  664.28   607.1  680.16     637  686.19     647   689.5
   838.5   760.8   888.9  777.76   979.6  806.31   999.8  814.44  1019.9  824.23
#Mann= 3 , 0 , 0
       0     .08       0   504.6    .045       0   529.6     .08       0
Bank Sta=504.6,529.6
XS Rating Curve= 0 ,0
Exp/Cntr=0.3,0.1

Type RM Length L Ch R = 1 ,286.6   ,177.6,186.6,195.6
XS GIS Cut Line= 4
      1590369.35      451235.928     1591411.302      450428.717
     1591393.792      449790.878     1591302.282      449476.954
#Sta/Elev= 30
    10.1  880.62   101.4  843.35   172.4  820.22   344.7  759.37   537.4  687.63
   567.8  672.35   577.9  670.82   598.2  673.33   628.6  671.42   699.6   670.1
   719.9  668.07   750.3  661.02   831.4  657.93    1095   656.9  1439.6  658.59
  1500.4  660.45  1682.7  661.21  1692.8  660.98  1710.7  658.07 1723.06  655.69
  1735.7  657.79  1763.7  668.09  1783.9   674.2  1844.7  685.55  1925.7   711.3
    1946  719.77    2075  782.27  2144.4   812.2  2233.6  845.76  2283.1  858.09
#Mann= 3 , 0 , 0
    10.1     .08       0  1710.7    .045       0  1735.7     .08       0
#XS Ineff= 2 , 0
          1678.3  695.79
Permanent Ineff=
       F       F
Bank Sta=1710.7,1735.7
XS Rating Curve= 0 ,0
Exp/Cntr=0.3,0.1

Type RM Length L Ch R = 1 ,100     ,100.1,100,99.9
XS GIS Cut Line= 5
     1590297.871      451439.948     1591136.598      450747.998
     1591448.499      450424.564     1591687.536      449707.453
     1591339.465      449418.092
#Sta/Elev= 30
       0   910.2    50.8  905.97   172.8  857.41   213.4  842.63   233.7  837.45
   335.3  819.02   416.6   795.9   477.6  774.43   558.9  743.04   640.2  701.43
   670.7   688.6   701.2  679.61   762.1     666   782.5  664.48   853.6  664.52
   945.1  658.19  1207.1   656.5  1818.8  659.91  1889.4  658.74  1917.2  655.76
  1929.7  654.74  1942.2  655.48  2050.7  679.76    2101  683.09  2161.5  694.96
  2191.8  707.79  2453.5  799.12  2574.2  845.35  2674.8  867.89  2745.2  879.76
#Mann= 3 , 0 , 0
       0     .08       0  1917.2    .045       0  1942.2     .08       0
#XS Ineff= 2 , 0
         1803.47  676.71
Permanent Ineff=
       F       F
Bank Sta=1917.2,1942.2
XS Rating Curve= 0 ,0
Exp/Cntr=0.3,0.1

Chan Stop Cuts=-1
Use User Specified Reach Order=0